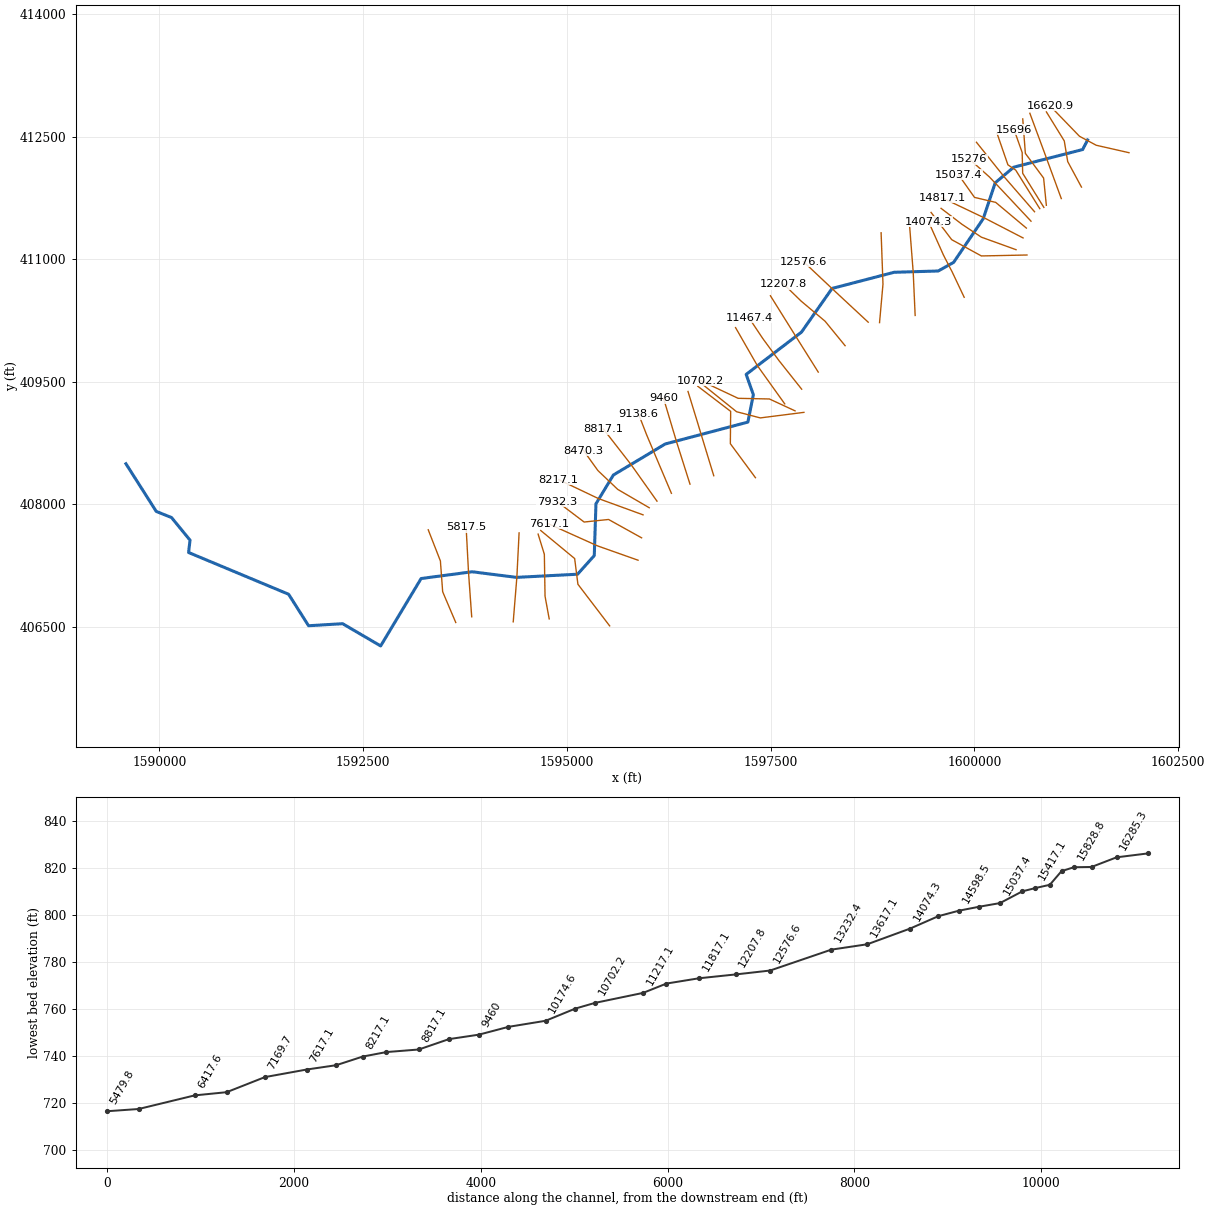
--- RFLICKCR.prj (project) ---

Proj Title=RFLICKCR
Current Plan=p01
Default Exp/Contr=0,0
English Units
Geom File=g01
Flow File=f01
Plan File=p01
BEGIN DESCRIPTION:
END DESCRIPTION:
DSS Export Rating Curves= 0
DSS Export Rating Curve Sorted= 0
DSS Export Volume Flow Curves= 0
DXF OffsetX= 0
DXF OffsetY= 0
DXF ScaleX= 0
DXF ScaleY= 0

--- RFLICKCR.p01 (plan) ---

Plan Title=Floodplain
Program Version=4.00
Geom File=g01
Flow File=f01
K Sum by GR=0
Std Step Tol=0.01
Critical Tol=0.01
Num of Std Step Trials=20
Max Error Tol=0.3
Flow Tol Ratio=0.001
Split Flow NTrial=30
Split Flow Tol=0.02
Split Flow Ratio=0.02
Log Output Level=0
Friction Slope Method=1
Unsteady Friction Slope Method=2
Unsteady Bridges Friction Slope Method=1
Global Log Level=0
CheckData=False
Run HTab=0
Run UNet=0
Run PostProcess=0
UNET Theta=0
UNET Theta Warmup=0
UNET ZTol=0
UNET ZSATol=0
UNET MxIter=0
UNET MaxInSteps=0
UNET DtIC=0
UNET DtMin=0
UNET MaxCRTS=0
UNET WFStab=0
UNET SFStab=0
UNET WFX=0
UNET SFX=0
UNET DSS MLevel=0
UNET DZMax Abort=0
UNET Convert EG Bridges=0
UNET Use Existing IB Tables=0
UNET Froude Limit=0
UNET Froude Power=0
Write IC File=0
Echo Input=False
Echo Output=False
Write Detailed=0

--- RFLICKCR.f01 (steady flow) ---

Flow Title=NFF Regression Equation
Program Version=4.00
Number of Profiles=1
Profile Names=P100yr
River Rch & RM=RFLICKCR,Main      ,16620.9
     366
River Rch & RM=RFLICKCR,Main      ,15570.8
     376
River Rch & RM=RFLICKCR,Main      ,15276
     450
River Rch & RM=RFLICKCR,Main      ,14378
     460
River Rch & RM=RFLICKCR,Main      ,14074.3
     557
River Rch & RM=RFLICKCR,Main      ,12576.6
     615
River Rch & RM=RFLICKCR,Main      ,10491.8
     655
River Rch & RM=RFLICKCR,Main      ,10174.6
     858
River Rch & RM=RFLICKCR,Main      ,7169.7
     946
River Rch & RM=RFLICKCR,Main      ,3853.6
    1037
River Rch & RM=RFLICKCR,Main      ,265.3
    1115
Boundary for River Rch & Prof#=RFLICKCR,Main      ,1
Up Type=0
Dn Type=3
Dn Slope=0.005237

--- RFLICKCR.g01 (geometry) ---

Geom Title=USGS 10m DEM
Program Version=4.00

River Reach=RFLICKCR        ,Main
Reach XY= 30
      1601388.52      412459.512     1601328.353      412342.469
      1600482.19      412126.483     1600255.235      411935.439
     1600107.912      411495.268     1599744.413      410961.163
     1599555.541      410855.901     1599015.792       410840.36
     1598253.344      410642.392     1597878.466      410108.591
     1597199.163      409590.328     1597287.496      409342.517
     1597220.264      409006.763     1596205.528       408738.68
     1595569.722      408359.105     1595356.186      408007.088
     1595335.493      407372.885     1595130.245      407145.051
     1594380.992       407106.47     1593837.567      407175.028
     1593210.885      407092.389     1592714.344      406267.333
     1592247.918      406539.416     1591829.836       406514.55
     1591584.887       406899.94     1590357.383      407410.911
     1590375.583      407561.568     1590147.924      407839.043
     1589960.974      407913.506      1589588.99      408496.668

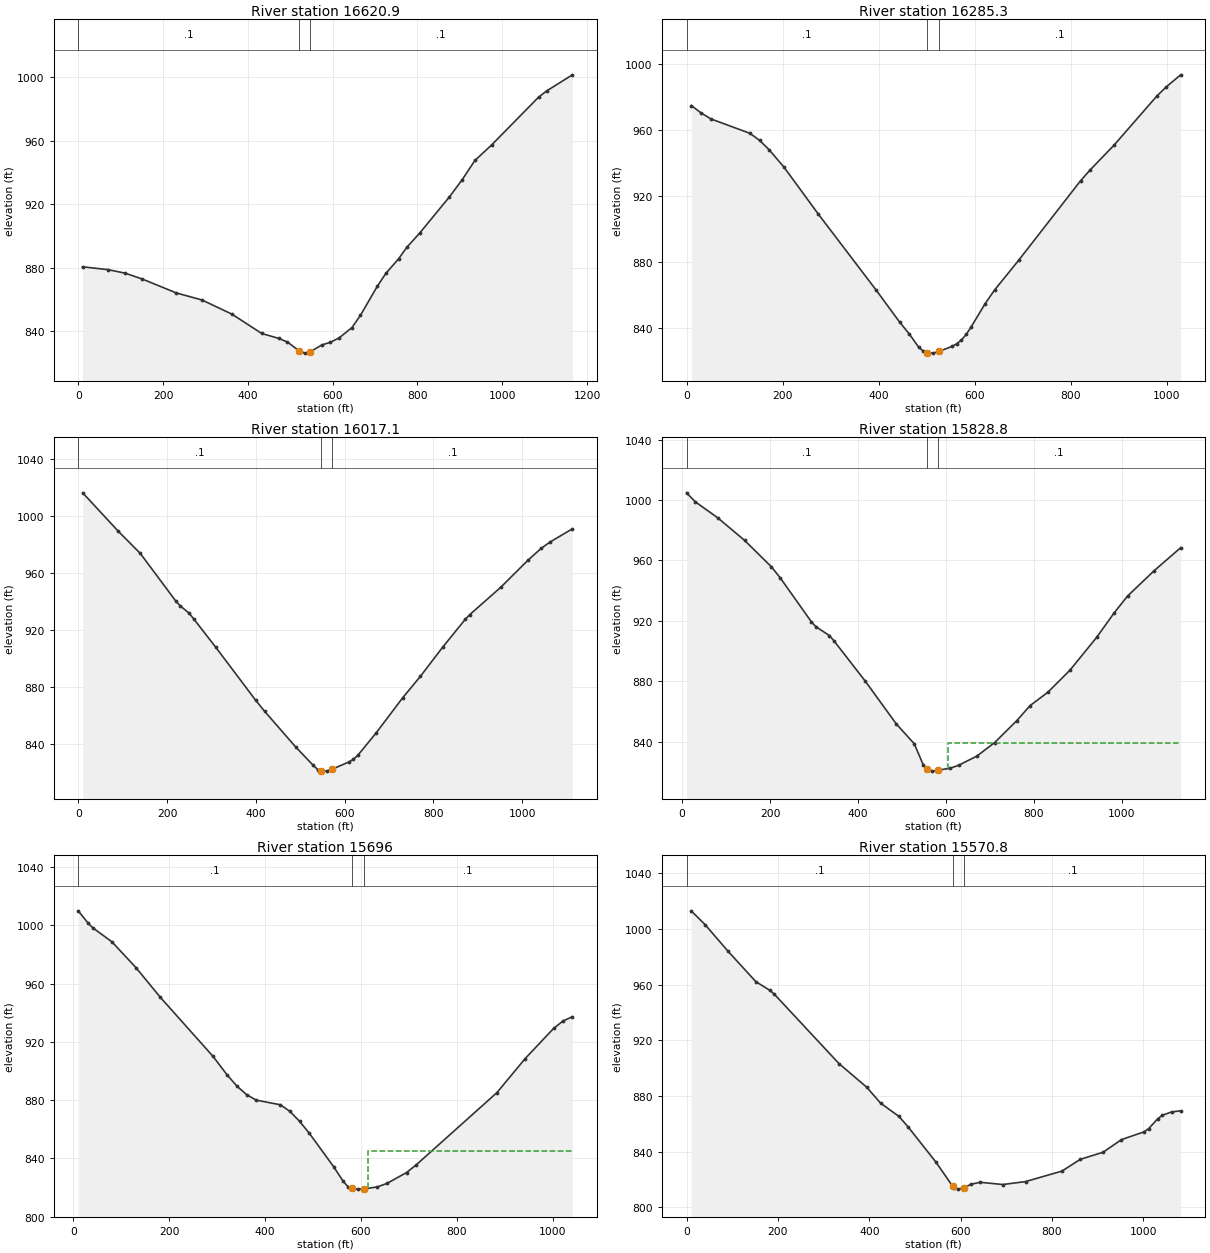
Type RM Length L Ch R = 1 ,16620.9 ,361.9,335.6,309.3
XS GIS Cut Line= 4
     1601896.875      412303.636     1601494.587       412394.88
     1601289.138      412504.724     1600927.055      412878.042
#Sta/Elev= 30
    10.1  880.66    70.4  878.88   110.7  876.66   150.9  872.99   231.4  864.23
   291.8   859.8   362.2  850.94   432.8  838.74   473.3  835.61   493.5  833.34
   521.6  827.69   534.1  826.39   546.6  827.16   574.6  831.53   594.8  833.23
   615.1  835.94   645.5  842.44   665.5  850.14   705.5  868.51   725.5  876.53
   755.5  885.69   775.5  893.12   805.5  901.94   875.5  924.67   905.5  935.44
   935.5  947.52   975.5  957.44  1085.5  987.29  1105.5   991.4  1165.5 1001.38
#Mann= 3 , 0 , 0
       0      .1       0   521.6    .045       0   546.6      .1       0
Bank Sta=521.6,546.6
XS Rating Curve= 0 ,0
Exp/Cntr=0.3,0.1

Type RM Length L Ch R = 1 ,16285.3 ,263.3,268.2,272.8
XS GIS Cut Line= 4
     1601313.369      411882.983      1601144.53      412195.334
      1601102.32      412448.591      1600882.83      412803.152
#Sta/Elev= 30
    10.1  974.62    30.4  970.14    50.7  966.54   131.9  957.82   152.2  953.52
   172.5  947.69   202.9  937.33   273.9  909.08   394.6  862.95   443.9  843.42
   463.7  836.33   483.4  828.27   493.3  825.87   500.6  825.09   513.1  824.72
   525.6  825.72   552.6  828.77   562.4  830.36   572.3  832.65   582.2  836.05
   592.1  840.37   621.7  854.72   641.6  863.04   691.2  880.85   820.3  929.08
   840.2  935.63   889.8  950.58   979.2  980.41     999  986.03  1028.8  993.23
#Mann= 3 , 0 , 0
       0      .1       0   500.6    .045       0   525.6      .1       0
Bank Sta=500.6,525.6
XS Rating Curve= 0 ,0
Exp/Cntr=0.3,0.1

Type RM Length L Ch R = 1 ,16017.1 ,180.4,188.3,196.1
XS GIS Cut Line= 3
     1601065.843      411742.363     1600876.285      412257.955
     1600680.224      412786.268
#Sta/Elev= 30
      10 1016.07    89.9  989.17   139.8  973.48   219.7  940.05   229.7  936.68
   249.7  931.54   259.7  927.68   309.6  907.64   399.5   870.4   419.5  862.71
   489.4  837.67   529.4  824.59   539.3  821.73   546.9  820.91   559.4  820.61
   571.9     822   609.7  827.07   619.8     829   629.8  831.81   670.1  847.14
   730.5  872.06   770.7  887.25     821  907.78   871.3  927.13   881.4  930.44
   951.8  949.82  1012.2  968.56  1042.4  977.04  1062.5  981.52  1112.9  990.81
#Mann= 3 , 0 , 0
       0      .1       0   546.9    .045       0   571.9      .1       0
Bank Sta=546.9,571.9
XS Rating Curve= 0 ,0
Exp/Cntr=0.3,0.1

Type RM Length L Ch R = 1 ,15828.8 ,149.8,132.8,115.8
XS GIS Cut Line= 4
     1600882.488      411660.156     1600848.943       411993.36
     1600624.953       412295.41     1600593.067      412717.278
#Sta/Elev= 30
    10.1 1004.71    30.4   998.7    81.2  988.14   142.1  973.25     203  955.79
   223.3   948.4   294.3  919.24   304.4  916.07   334.9  910.27   345.1  906.87
   416.2  880.22   487.3  851.69     528  838.62   548.3   824.8   556.1  822.23
   568.7   820.5   581.1   821.1   609.3  822.36   629.6  824.47   670.3  830.43
   710.9  839.42   761.3  853.96   791.5  863.88   831.8  872.69   882.2  887.35
   942.6  908.96   982.9  925.33  1013.1  936.39  1073.6  953.16    1134  968.43
#Mann= 3 , 0 , 0
    10.1      .1       0   556.1    .045       0   581.1      .1       0
#XS Ineff= 2 , 0
                          605.74          839.42
Permanent Ineff=
       F       F
Bank Sta=556.1,581.1
XS Rating Curve= 0 ,0
Exp/Cntr=0.3,0.1

Type RM Length L Ch R = 1 ,15696   ,97.3,125.3,153
XS GIS Cut Line= 4
     1600852.038      411634.411     1600592.109      412052.154
      1600585.92      412305.894       1600486.9      412584.389
#Sta/Elev= 30
      10 1010.07    30.1  1001.8    40.2  998.43    80.3  988.77   130.5  971.03
   180.7  950.88   291.2  910.09   321.3  897.07   341.4  889.56   361.5  883.71
   381.6  879.97   431.8   876.8   451.8  872.26   471.9  865.43     492  857.35
   542.8  834.33   563.1  824.17   573.2   820.4     581  819.37   593.5  818.83
     606  818.95   634.1  820.35   654.4  822.76   695.1  830.21   715.4   835.5
   883.8  885.15   942.9  908.59    1002  929.21  1021.7  934.35  1041.4  937.31
#Mann= 3 , 0 , 0
      10      .1       0     581    .045       0     606      .1       0
#XS Ineff= 2 , 0
                          614.34           844.9
Permanent Ineff=
       F       F
Bank Sta=581,606
XS Rating Curve= 0 ,0
Exp/Cntr=0.3,0.1

Type RM Length L Ch R = 1 ,15570.8 ,160.9,153.7,145.3
XS GIS Cut Line= 4
     1600801.855      411618.843     1600506.762      412090.225
     1600410.953      412155.375      1600276.82      412542.445
#Sta/Elev= 30
    10.1 1012.95    40.4 1003.11      91  983.86   151.7  962.06     182  955.91
   192.1  953.08   333.7  903.19   394.3  886.26   424.7  874.81   465.1   865.2
   485.4  857.55     546  832.36   582.3  815.16   585.1     814   594.8  813.01
   607.3  814.11   623.7  816.61     643  817.93     692  816.32   741.9  818.42
   821.9  825.99   861.8  834.43   911.8  839.51   951.8  848.57  1001.7  854.21
  1011.7  856.56  1031.7  863.69  1041.7   866.1  1061.7  868.48  1081.6   869.3
#Mann= 3 , 0 , 0
       0      .1       0   582.3    .045       0   607.3      .1       0
Bank Sta=582.3,607.3
XS Rating Curve= 0 ,0
Exp/Cntr=0.3,0.1

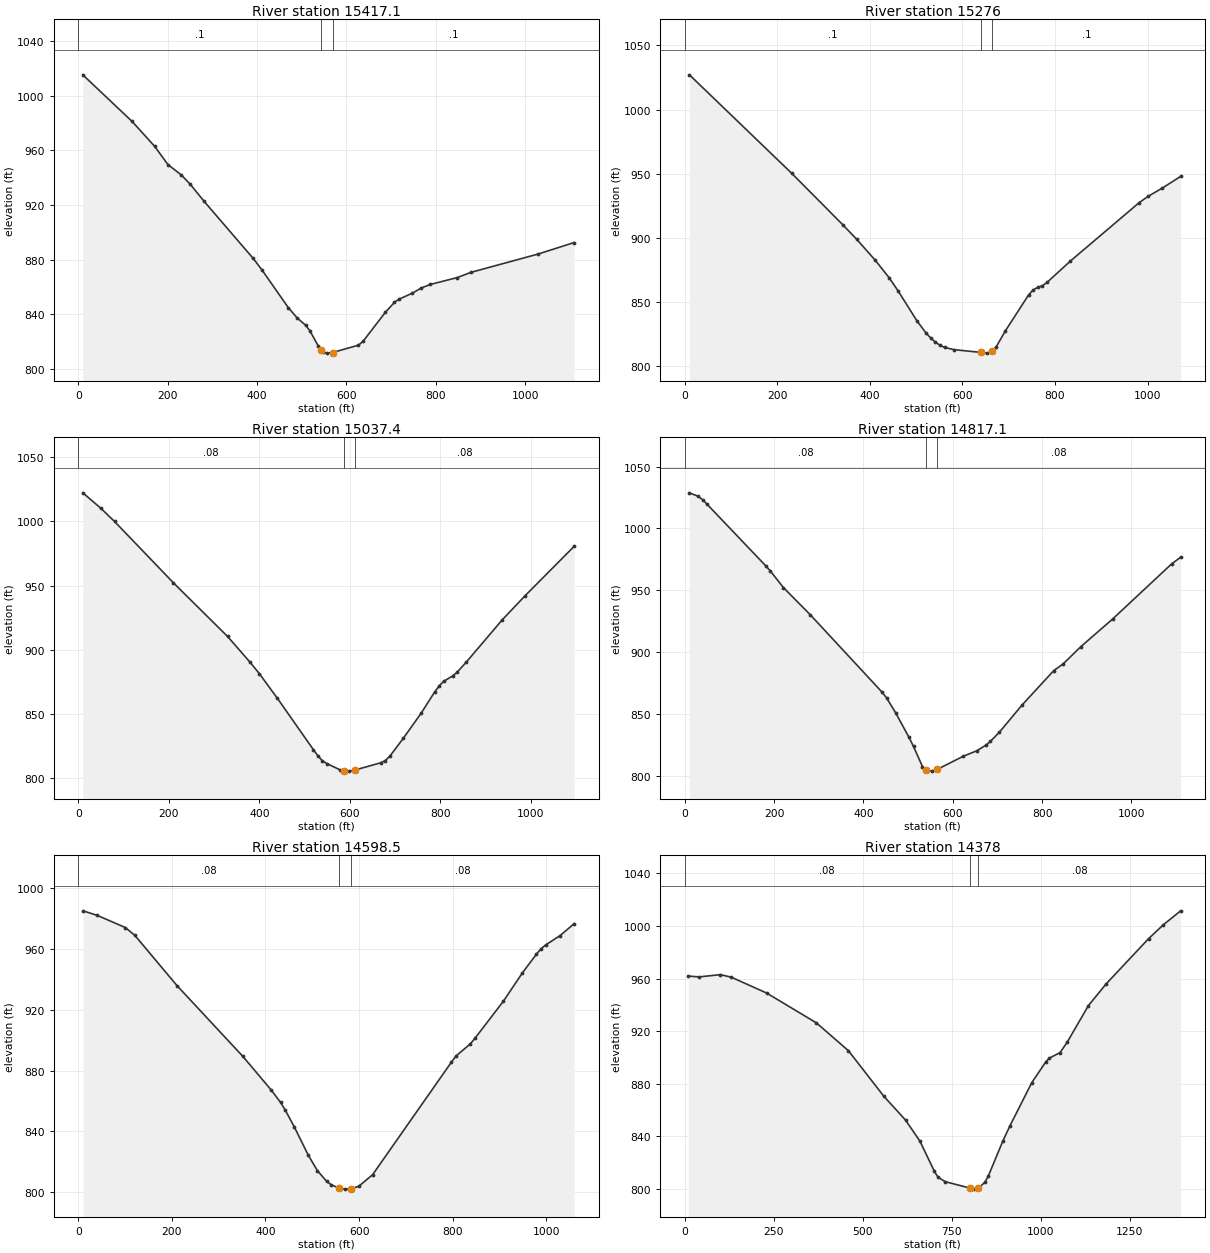
Type RM Length L Ch R = 1 ,15417.1 ,140.4,141.1,142.9
XS GIS Cut Line= 4
     1600737.408       411581.45     1600453.852      411906.431
     1600371.511      412000.802      1600024.68      412431.595
#Sta/Elev= 30
      10 1015.39   120.4  981.23   170.5  963.15   200.6  949.64   230.7     942
   250.8  935.14   280.8  923.02   391.2  881.02   411.2  872.41   469.8     845
   489.1  837.61   508.4  832.12     518  828.09   537.3  816.68     544  813.87
   546.9  812.65   556.5  811.63     569  812.08   626.9  817.46     637  820.19
   687.3   841.6   707.4  848.77   717.4   851.1   747.6  855.54   767.7  859.35
   787.8  861.92   848.2  866.97   878.3  870.74  1029.2   884.2  1109.6   892.6
#Mann= 3 , 0 , 0
       0      .1       0     544    .045       0     569      .1       0
Bank Sta=544,569
XS Rating Curve= 0 ,0
Exp/Cntr=0.3,0.1

Type RM Length L Ch R = 1 ,15276   ,222.7,238.7,254.6
XS GIS Cut Line= 4
     1600694.549      411465.548     1600330.473      411852.618
     1600184.843      412005.913     1599939.571      412224.358
#Sta/Elev= 30
      10 1027.14   230.6  950.52   340.9  910.43     371  899.13   411.1  882.77
   441.2  869.14   461.2  858.54   501.3  835.53   521.4   825.8   531.4  821.97
   541.5  818.82   551.5  816.25   561.6  814.66   581.7   812.9   639.7  810.79
   652.2  810.21   662.3   811.2   664.7  812.06   672.4  814.83   692.5  827.49
   742.8  855.57   752.8  859.51   762.7  861.51   772.7  862.75   782.6   865.3
   832.4  881.76   981.7   927.5  1001.6  932.55  1031.5  938.81  1071.3  947.94
#Mann= 3 , 0 , 0
       0      .1       0   639.7    .045       0   664.7      .1       0
Bank Sta=639.7,664.7
XS Rating Curve= 0 ,0
Exp/Cntr=0.3,0.1

Type RM Length L Ch R = 1 ,15037.4 ,227.2,220.3,214.3
XS GIS Cut Line= 4
     1600637.063      411381.235      1600261.49       411695.49
     1600000.889      411756.808     1599805.437      412032.739
#Sta/Elev= 30
      10 1022.32      50 1010.19      80  999.98   209.9  952.19   329.8  910.26
   379.8  890.03   399.8  881.34   439.7  862.09   519.5   821.9   529.4  817.12
   539.3  813.31   549.2  811.06   578.9  806.12   586.3  805.48   598.8  805.21
   611.3  806.06   668.2  811.73   678.1  813.45     688  816.69   717.8  830.69
   757.4  850.33   787.3  866.93   797.2  871.61   807.1  875.26     827  879.45
     837  882.37   856.9  890.11   936.4  923.13   986.2  941.68  1095.6  980.59
#Mann= 3 , 0 , 0
       0     .08       0   586.3    .045       0   611.3     .08       0
Bank Sta=586.3,611.3
XS Rating Curve= 0 ,0
Exp/Cntr=0.3,0.1

Type RM Length L Ch R = 1 ,14817.1 ,221.6,218.6,214.7
XS GIS Cut Line= 3
     1600596.882      411260.615     1600114.971      411508.966
     1599601.967       411752.49
#Sta/Elev= 30
      10 1028.76    30.1 1025.94    40.2 1023.05    50.2 1019.39   180.7  969.91
   190.8  965.87   220.9  952.09   281.1  930.07   441.7  867.53   451.8  862.82
   471.9  850.96     502  830.91     512  823.65   532.1  807.33   539.8  804.58
   542.1  803.76   552.3  803.68   564.8  805.04   623.3  815.68   653.7  820.16
     674  824.62   684.1  827.71   704.4  835.21   755.1  857.18   826.1  885.02
   846.4   890.2   886.9  904.44   957.9  926.75  1089.7  971.23    1110  976.66
#Mann= 3 , 0 , 0
       0     .08       0   539.8    .045       0   564.8     .08       0
Bank Sta=539.8,564.8
XS Rating Curve= 0 ,0
Exp/Cntr=0.3,0.1

Type RM Length L Ch R = 1 ,14598.5 ,218,220.5,222.9
XS GIS Cut Line= 4
     1600510.594      411116.802     1600085.201      411270.097
     1599847.593      411427.224     1599590.824      411622.675
#Sta/Elev= 30
      10  985.09    40.2  982.11   100.5  974.09   120.6  969.02     211  935.83
   351.7   889.3     412  867.28   432.1   859.1   442.1  854.06     462  842.67
   491.5  824.28   511.1  814.06   530.8  807.09   540.6  804.85   557.5   802.6
     570  801.98   582.5  802.11   599.5  803.88     629  811.51   797.5  885.58
   807.6  889.67   837.9  897.59     848  901.35   908.5  925.64   948.8  944.12
   979.1   956.6   989.1  960.18   999.2  962.73  1029.5  968.77  1059.7  976.64
#Mann= 3 , 0 , 0
       0     .08       0   557.5    .045       0   582.5     .08       0
Bank Sta=557.5,582.5
XS Rating Curve= 0 ,0
Exp/Cntr=0.3,0.1

Type RM Length L Ch R = 1 ,14378   ,320.3,303.7,287.1
XS GIS Cut Line= 4
     1600644.728      411051.651     1600085.201      411040.154
     1599721.125      411239.438     1599468.188      411572.854
#Sta/Elev= 30
      10  961.87      40  961.22    99.9  962.94   129.9  961.08   229.9  948.96
   369.8  926.22   459.7  905.06   559.6  870.25   620.4  852.18   660.9  836.03
   701.4  813.14   711.5  808.69   731.7  805.33   800.2  800.51   812.7  799.64
   825.2  800.56   843.1   804.8   853.2  809.84   893.7  836.29     914  848.04
   974.7  880.58  1014.6  896.66  1024.5  899.39  1054.4  903.61  1074.3  911.42
  1134.1  939.38  1183.9  955.89  1303.5  990.43  1343.4 1000.61  1393.2 1011.54
#Mann= 3 , 0 , 0
       0     .08       0   800.2    .045       0   825.2     .08       0
Bank Sta=800.2,825.2
XS Rating Curve= 0 ,0
Exp/Cntr=0.3,0.1

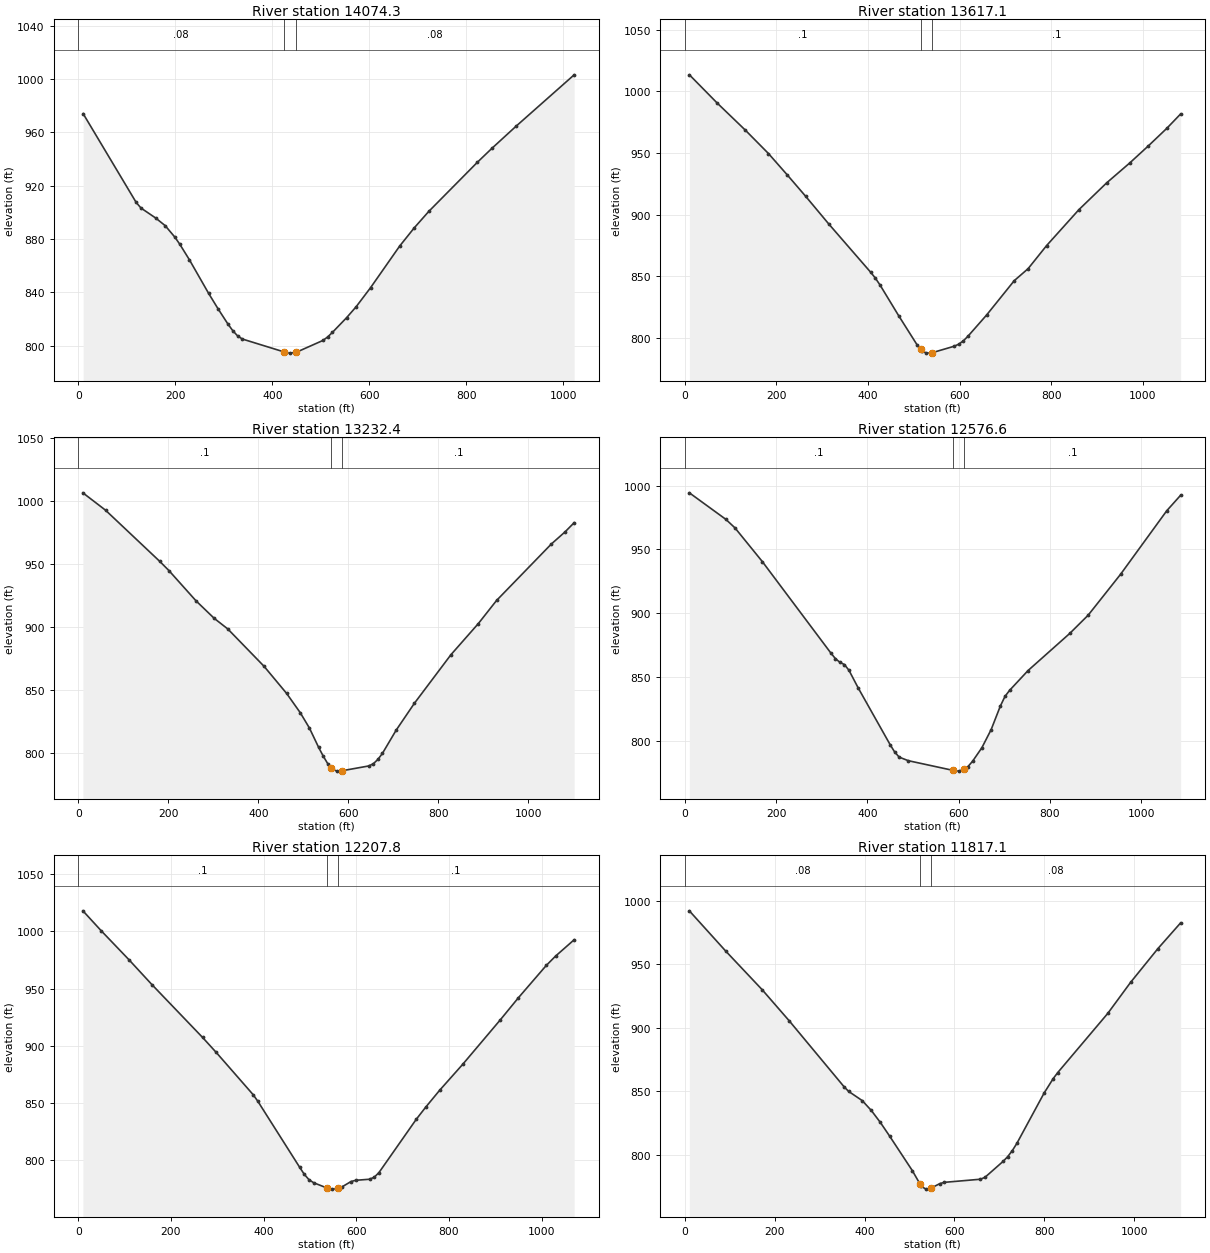
Type RM Length L Ch R = 1 ,14074.3 ,469.4,457.2,446
XS GIS Cut Line= 4
      1599874.42       410534.28     1599724.957      410848.535
     1599621.483      411047.819     1599437.529      411457.883
#Sta/Elev= 30
     9.9  973.94   119.3   907.3   129.3   903.1   159.1  895.75     179  889.95
   198.8   881.4   208.8  876.17   228.7   864.5   268.4  839.24   288.3   827.4
   308.2  816.23   318.2  811.24   328.1  807.32     338  804.91   423.4  795.31
   435.9  794.33   448.4  794.83   504.2  803.85     514  806.49   523.7  809.87
     553  820.93   572.5  829.05   602.5  843.49   662.4  874.65   692.4  888.29
   722.3   900.6   822.2  937.35   852.2  947.83   902.1  964.45    1022 1003.05
#Mann= 3 , 0 , 0
       0     .08       0   423.4    .045       0   448.4     .08       0
Bank Sta=423.4,448.4
XS Rating Curve= 0 ,0
Exp/Cntr=0.3,0.1

Type RM Length L Ch R = 1 ,13617.1 ,384.9,384.7,383.4
XS GIS Cut Line= 3
     1599272.737      410312.003     1599248.943      410839.185
     1599205.932      411392.564
#Sta/Elev= 30
    10.1 1013.42      71  990.43   131.9  968.66   182.7  949.57   223.3  932.43
   263.9   914.9   314.6  892.34   405.9  853.27   416.1  848.54   426.2  843.01
   466.8  818.18   507.4  794.29   515.2  790.76   517.6  789.68   527.7  787.66
   540.2     788   588.3  793.25   598.4  794.94   608.5  797.68   618.5  801.42
   658.9  818.49   719.5  846.46   749.7  856.16   790.1  874.89   860.7  904.06
   921.3  925.79   971.8  941.96  1012.1  955.69  1052.5  969.97  1082.8  981.67
#Mann= 3 , 0 , 0
       0      .1       0   515.2    .045       0   540.2      .1       0
Bank Sta=515.2,540.2
XS Rating Curve= 0 ,0
Exp/Cntr=0.3,0.1

Type RM Length L Ch R = 1 ,13232.4 ,634,655.8,677.7
XS GIS Cut Line= 3
     1598835.862      410224.167     1598878.002       410695.24
     1598855.008       411323.75
#Sta/Elev= 30
    10.1 1006.44    60.4  992.66   181.1  951.94   201.3  944.69   261.6  920.62
   301.9  906.76   332.1  898.32   412.6   868.7   462.9   847.1   493.2  831.78
   513.5  819.64   533.8  804.42     544  797.44   554.1   791.4   561.9   788.1
   564.3  787.08   574.4  785.37   586.9  785.72   645.4  789.48   655.5  791.22
   665.7  794.65   675.8  799.47   706.3  817.89   746.8  839.24     828  877.82
   888.9  902.55   929.4  920.91  1051.2  965.78  1081.6   975.4  1101.9  982.72
#Mann= 3 , 0 , 0
       0      .1       0   561.9    .045       0   586.9      .1       0
Bank Sta=561.9,586.9
XS Rating Curve= 0 ,0
Exp/Cntr=0.3,0.1

Type RM Length L Ch R = 1 ,12576.6 ,366.5,368.8,371.2
XS GIS Cut Line= 3
     1598696.644      410229.596     1598293.364      410603.334
     1597902.021      410970.875
#Sta/Elev= 30
      10  994.34      90  973.57     110  966.88   169.9  940.52   319.9  869.02
   329.9  864.62   339.9  861.66   349.9  859.88   359.9  855.36   379.9  841.67
   449.9  797.26   459.9  791.46   469.9  787.41   489.9  784.63     588  777.04
   600.5  776.46     613  777.91   620.7  780.05   630.9  784.28   651.1  794.78
   671.4  808.95   691.6  827.42   701.8  834.99   711.9  839.72   752.4  855.24
   843.6  884.22   884.1  898.57     955  930.53  1056.3  980.31  1086.7  992.45
#Mann= 3 , 0 , 0
       0      .1       0     588    .045       0     613      .1       0
Bank Sta=588,613
XS Rating Curve= 0 ,0
Exp/Cntr=0.3,0.1

Type RM Length L Ch R = 1 ,12207.8 ,400,390.7,381.2
XS GIS Cut Line= 4
     1598413.087      409942.059     1598167.576      410241.463
     1597874.159      410486.975     1597658.588      410696.558
#Sta/Elev= 30
     9.9 1017.98    49.6 1000.47   109.2  975.29   158.8  953.54   268.1  907.39
   297.8   894.2   377.3  857.37   387.2  851.76   477.8   793.9   487.9  787.69
   497.9  783.07     508  780.38   535.8  775.95   548.3   774.8   560.8  775.39
   568.4  776.55   588.6  781.42   598.6   782.5   628.8  783.44   638.9  785.22
     649  789.26   729.5   835.8   749.6  846.25   779.8  861.08   829.9  883.89
   910.1  922.29   950.2   942.1  1010.3   970.3  1030.3  978.43  1070.4  992.71
#Mann= 3 , 0 , 0
       0      .1       0   535.8    .045       0   560.8      .1       0
Bank Sta=535.8,560.8
XS Rating Curve= 0 ,0
Exp/Cntr=0.3,0.1

Type RM Length L Ch R = 1 ,11817.1 ,347.6,349.7,351.8
XS GIS Cut Line= 3
     1598083.743      409618.702     1597797.731      410072.519
      1597496.91      410552.843
#Sta/Elev= 30
    10.1  992.07    91.1  960.39   172.1  930.04   232.8  905.37   354.2  853.75
   364.4  850.08   394.7  842.82     415  835.05   435.2  825.58   455.5     815
   506.1  787.81   523.9  776.85   526.3  775.37   536.4  773.17   548.9  774.15
   566.8  777.39   576.9  778.49   657.9  780.96     668  782.49   708.5  795.09
   718.6  798.79   728.7  803.45   738.8  809.13   799.6  848.83   819.8  860.16
   829.9  864.89   941.2  911.43   991.8  935.77  1052.6  962.33  1103.2   982.6
#Mann= 3 , 0 , 0
       0     .08       0   523.9    .045       0   548.9     .08       0
Bank Sta=523.9,548.9
XS Rating Curve= 0 ,0
Exp/Cntr=0.3,0.1

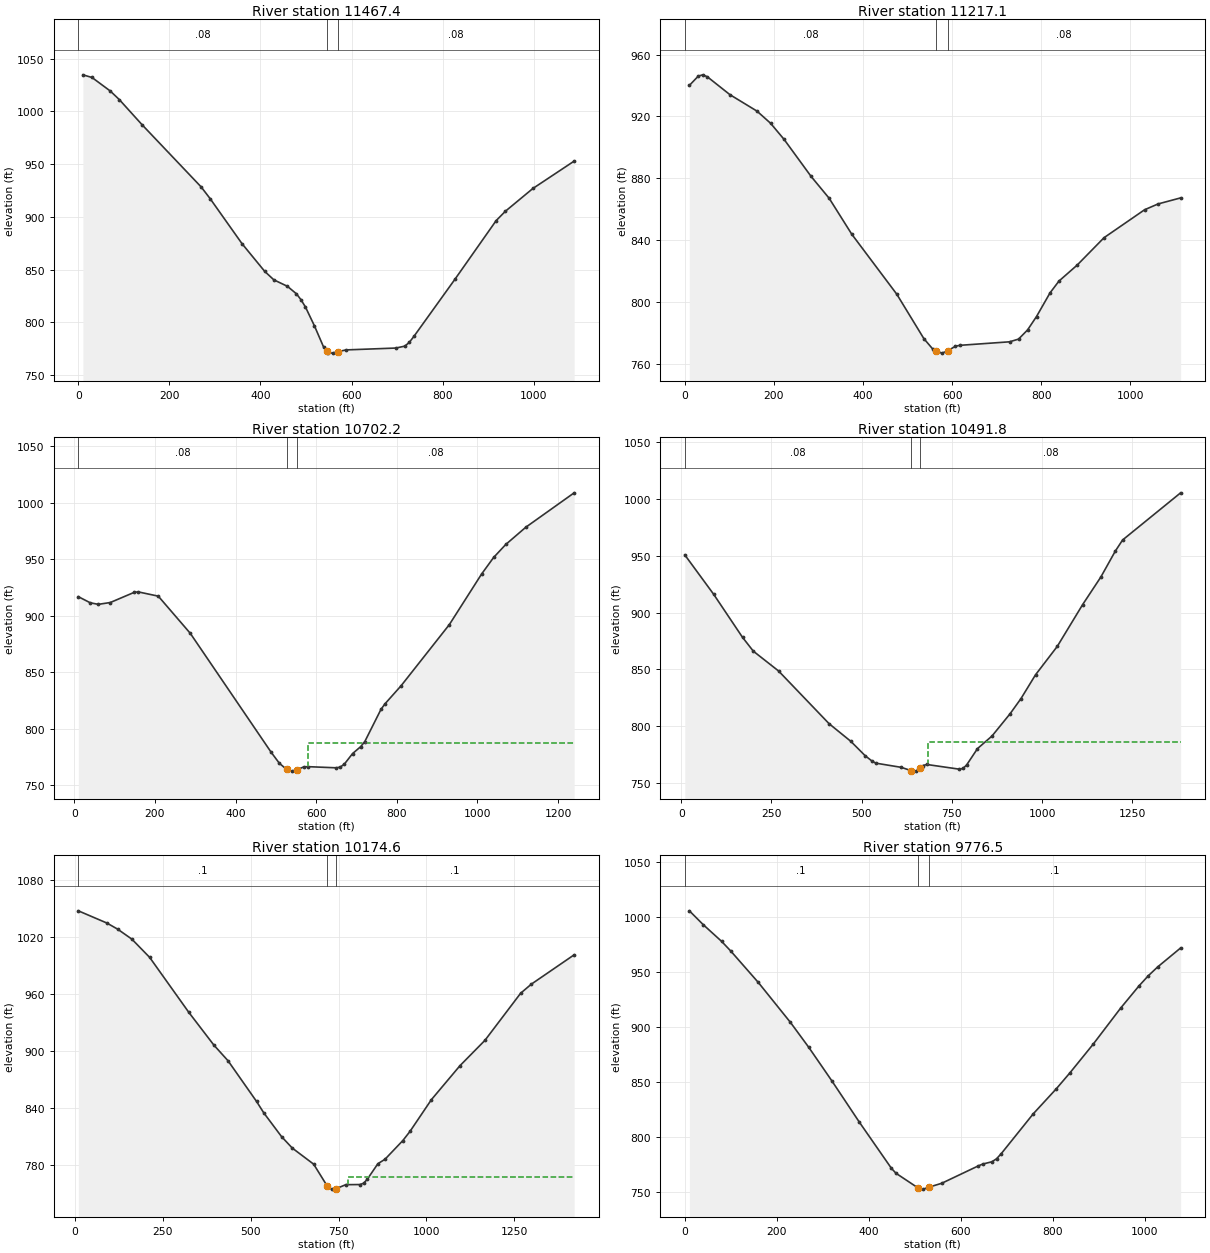
Type RM Length L Ch R = 1 ,11467.4 ,250.7,250.3,247.3
XS GIS Cut Line= 4
     1597880.127       409409.62     1597600.447      409761.217
     1597400.676      410032.907     1597232.868      410284.619
#Sta/Elev= 30
      10 1034.54      30 1032.03    69.9 1019.29    89.9 1011.13   139.8  987.35
   269.6  928.42   289.5  917.25   359.4  874.66   409.3  848.38   429.3  840.37
   459.2  834.21     479  827.12   488.9  821.56   498.9  814.56   518.7  796.61
   538.5  776.86   545.9  772.72   548.5  771.27   558.4  770.91   570.9  772.36
   588.1  773.96   697.2  775.72   717.1  777.53     727  781.14   736.9  786.68
   826.8  840.66   917.6   896.4   937.8  905.25   998.3  926.86    1089  952.81
#Mann= 3 , 0 , 0
       0     .08       0   545.9    .045       0   570.9     .08       0
Bank Sta=545.9,570.9
XS Rating Curve= 0 ,0
Exp/Cntr=0.3,0.1

Type RM Length L Ch R = 1 ,11217.1 ,489.3,514.9,543.2
XS GIS Cut Line= 3
     1597672.365      409229.825     1597336.055      409698.792
     1597069.111      410163.099
#Sta/Elev= 30
    10.1  940.05    30.4  946.15    40.5  946.94    50.6  945.67   101.2  934.12
     162  923.47   192.4  915.64   222.7  905.22   283.5   881.2     324  867.08
   374.6  843.89   475.8  805.01   536.6  776.27   556.8  769.46   564.6  768.02
   577.1  766.93   589.6  768.36   607.4   771.4   617.5  771.98   728.7  774.25
   748.9  775.99   769.1  781.89   789.3   790.6   819.6  805.89   839.8  813.58
   880.2  823.78   940.9  841.61  1031.8  859.66  1062.1  863.43  1112.7  867.34
#Mann= 3 , 0 , 0
       0     .08       0   564.6    .045       0   589.6     .08       0
Bank Sta=564.6,589.6
XS Rating Curve= 0 ,0
Exp/Cntr=0.3,0.1

Type RM Length L Ch R = 1 ,10702.2 ,216.8,210.4,204
XS GIS Cut Line= 4
     1597799.483      409144.158      1597484.58      409289.757
     1597101.019      409297.748     1596640.004      409514.126
#Sta/Elev= 30
     9.9  916.83    39.6  911.42    59.5  910.07    89.2  911.68   148.7   920.7
   158.6  921.07   208.2   917.3   287.5   884.5   488.3  779.29   508.5  769.62
   526.3   764.3   538.8  762.67   551.3  763.71     569   766.4   579.1  766.62
   649.8   765.6   659.9  766.24     670  768.99   690.2   778.2   710.4  784.34
   720.5  788.81   760.5  817.17   770.5  822.13   810.5  838.11   930.3  892.21
  1010.2  936.86  1040.1  951.52  1070.1  962.96    1120  978.25  1239.8 1008.62
#Mann= 3 , 0 , 0
     9.9     .08       0   526.3    .045       0   551.3     .08       0
#XS Ineff= 2 , 0
                          579.41          787.29
Permanent Ineff=
       F       F
Bank Sta=526.3,551.3
XS Rating Curve= 0 ,0
Exp/Cntr=0.3,0.1

Type RM Length L Ch R = 1 ,10491.8 ,354.5,317.2,283.2
XS GIS Cut Line= 4
     1597908.095      409125.944     1597372.708      409058.022
     1597081.041      409133.935     1596657.526      409473.546
#Sta/Elev= 30
      10   950.8    89.9  916.12   169.9  878.16   199.9  865.94   269.8  848.51
   409.8  802.04   469.7  786.59   509.7  773.85   529.7  768.87   539.7  767.25
     610  763.56   637.7  760.63   650.2  760.24   662.7  763.06   670.3  765.16
   680.3  766.11   770.7  761.96   780.8   762.6   790.8   765.6     821  780.07
   861.2  791.17   911.4  810.82   941.6   824.2   981.8  845.12  1042.1  870.16
  1112.5  907.05  1162.8  931.28    1203  954.18  1223.1  963.93  1383.9 1005.49
#Mann= 3 , 0 , 0
      10     .08       0   637.7    .045       0   662.7     .08       0
#XS Ineff= 2 , 0
                          682.72          785.81
Permanent Ineff=
       F       F
Bank Sta=637.7,662.7
XS Rating Curve= 0 ,0
Exp/Cntr=0.3,0.1

Type RM Length L Ch R = 1 ,10174.6 ,389.7,398.1,406.5
XS GIS Cut Line= 4
     1597312.776      408326.858     1597005.128      408742.383
     1597009.124       409137.93     1596605.585      409445.578
#Sta/Elev= 30
    10.1 1047.68    91.2 1034.86   121.7 1028.46   162.2 1017.95   212.9  998.73
   324.4  940.86   395.4  906.57   435.9  889.97     517  847.19   537.3   835.3
     588  810.24   618.4  798.24   679.3  781.28   717.5  758.48     730  755.05
   742.5  755.45   770.6  759.73   811.2  759.87   821.3  761.26   831.4  765.26
   861.9  781.77   882.2  786.48   932.9  806.15   953.2  815.75  1014.1  849.15
  1095.3  884.85  1166.3   911.5  1267.8  961.01  1298.2  970.56    1420 1001.43
#Mann= 3 , 0 , 0
    10.1      .1       0   717.5    .045       0   742.5      .1       0
#XS Ineff= 2 , 0
                          776.35          767.63
Permanent Ineff=
       F       F
Bank Sta=717.5,742.5
XS Rating Curve= 0 ,0
Exp/Cntr=0.3,0.1

Type RM Length L Ch R = 1 ,9776.5  ,316.2,316.5,316.4
XS GIS Cut Line= 4
     1596801.361      408350.831     1596681.498      408742.383
     1596597.594      409018.067     1596485.722      409381.652
#Sta/Elev= 30
      10 1005.32      40  992.77    79.9  977.64    99.9  968.81   159.8  940.27
   229.7  903.96   269.7  881.21   319.6  850.93   379.5  813.34   449.2   771.4
   459.2  766.87   506.3  753.79   508.9  753.07   518.8  752.46   531.3   754.3
   558.5  757.75     638  773.54     648  775.25   667.8  777.32   677.8  780.01
   687.7   784.5   757.7  820.91   807.8  843.63   837.8  858.31   887.9  884.12
   947.9  917.05     988  937.32    1008  946.39    1028  954.28  1078.1  971.58
#Mann= 3 , 0 , 0
       0      .1       0   506.3    .045       0   531.3      .1       0
Bank Sta=506.3,531.3
XS Rating Curve= 0 ,0
Exp/Cntr=0.3,0.1

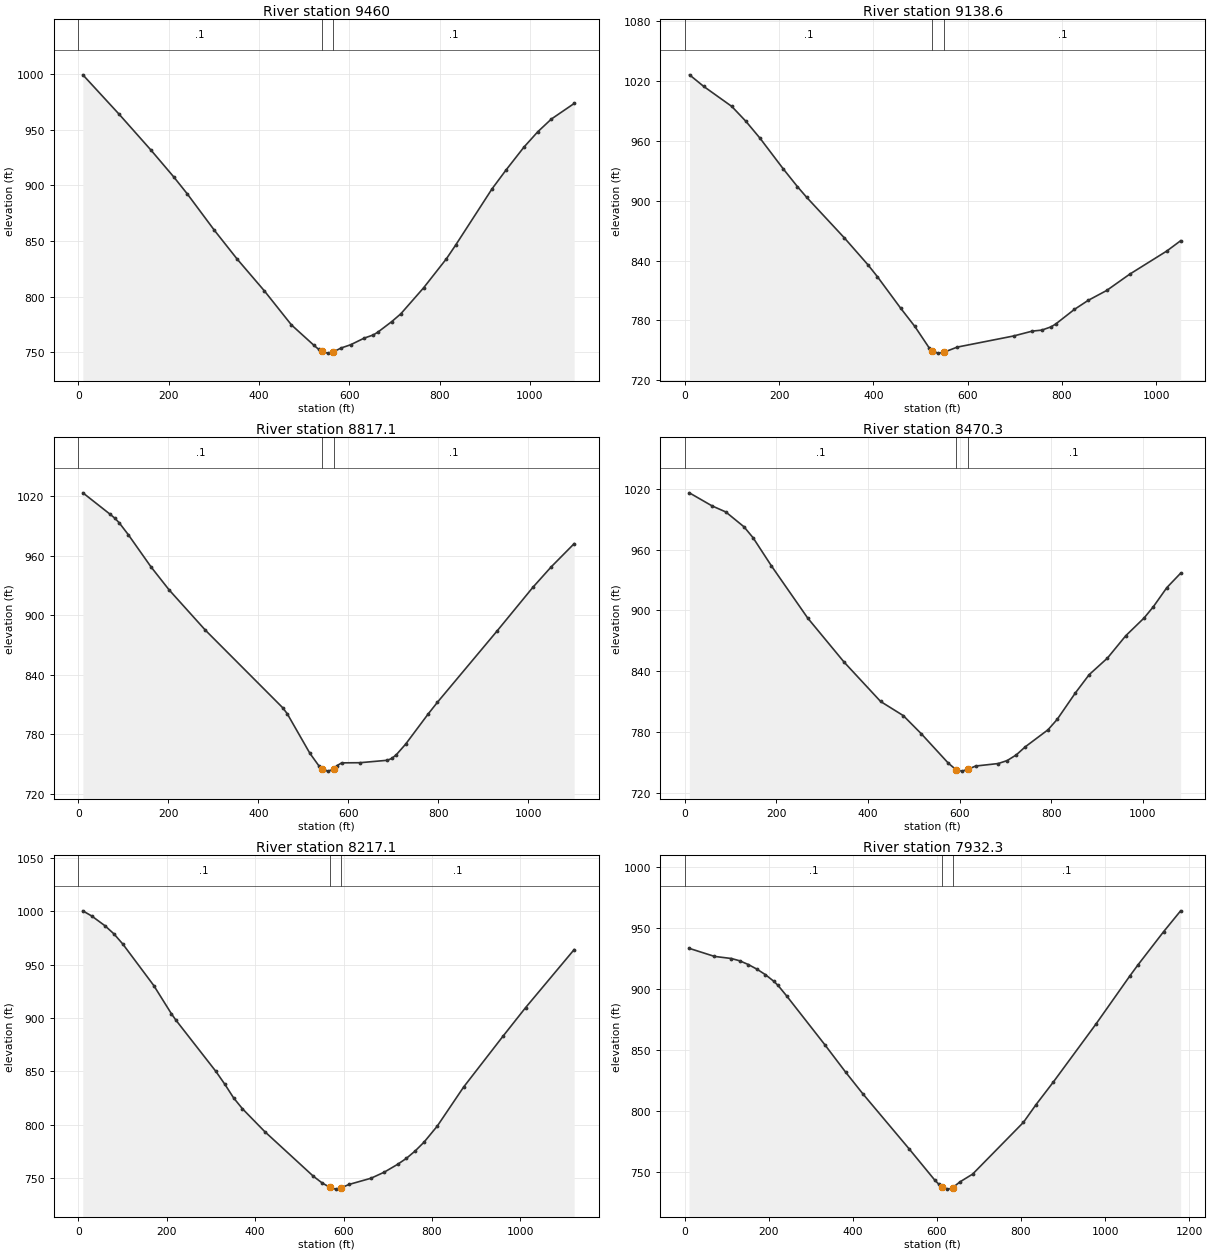
Type RM Length L Ch R = 1 ,9460    ,318.6,321.4,324.6
XS GIS Cut Line= 3
     1596510.045      408247.063     1596342.657      408773.324
     1596186.091      409295.953
#Sta/Elev= 30
      10  999.41    90.4  963.94   160.7  931.77   210.9  907.78     241  892.47
   301.2  859.62   351.4  833.84   411.7  805.22   471.9  774.48   522.1     756
   532.2  752.52   539.7  750.64   552.2  749.13   564.7  750.32   582.5  753.84
   602.8  756.65   633.1  762.65   653.3  765.52   663.4  768.06   693.7  777.41
   713.9  784.44   764.4  807.83   814.9  833.95   835.1  846.09     916  896.88
   946.3  913.46   986.7  934.43    1017   948.1  1047.3  959.64  1097.8  973.64
#Mann= 3 , 0 , 0
       0      .1       0   539.7    .045       0   564.7      .1       0
Bank Sta=539.7,564.7
XS Rating Curve= 0 ,0
Exp/Cntr=0.3,0.1

Type RM Length L Ch R = 1 ,9138.6  ,315.5,321.5,328.8
XS GIS Cut Line= 4
     1596281.955      408135.077     1596122.138      408510.648
     1595978.303      408850.259     1595878.417      409105.967
#Sta/Elev= 30
      10 1026.18    39.8 1014.68    99.6  994.52   129.4  979.68   159.3  962.77
   209.1  931.73   238.9   914.1   258.8  903.22   338.5  862.68   388.2  835.89
   408.2  824.01     458  792.12   487.9  773.93   517.8  752.79   525.2  749.62
   527.8   748.5   537.7  747.22   550.2  748.22   577.6  753.24   697.2   764.4
   737.1   769.3     757  770.28     777  773.61   786.8  776.48     826  790.97
   855.4  800.09   894.6     810   943.7  826.41  1022.1  849.54  1051.5  859.88
#Mann= 3 , 0 , 0
       0      .1       0   525.2    .045       0   550.2      .1       0
Bank Sta=525.2,550.2
XS Rating Curve= 0 ,0
Exp/Cntr=0.3,0.1

Type RM Length L Ch R = 1 ,8817.1  ,341.5,346.7,350.8
XS GIS Cut Line= 3
     1596104.891      408039.392     1595783.349      408491.478
     1595447.028      408922.467
#Sta/Elev= 30
    10.1 1023.38    70.6 1001.78    80.7  997.97    90.8  993.18     111   981.2
   161.4  948.75   201.7  925.51   282.4  884.83   453.9  806.78     464  800.75
   514.4  760.78   534.6  748.03   542.3  745.07   544.7  744.14   554.8  742.81
   564.9  744.45   567.3   745.4     575  748.43   585.1  751.14   625.6   751.3
   686.4  753.75   696.5  755.63   706.6  759.45   726.9   769.9   777.5  800.62
   797.7   812.2   929.4  883.63  1010.3  928.39  1050.8  948.87  1101.5  972.13
#Mann= 3 , 0 , 0
       0      .1       0   542.3    .045       0   567.3      .1       0
Bank Sta=542.3,567.3
XS Rating Curve= 0 ,0
Exp/Cntr=0.3,0.1

Type RM Length L Ch R = 1 ,8470.3  ,241.9,253.3,262
XS GIS Cut Line= 4
     1596010.016      407958.654     1595622.959      408183.397
     1595379.488      408414.383     1595204.688      408657.855
#Sta/Elev= 30
     9.9 1015.82    59.7 1002.91    89.5  996.99   129.3  982.35   149.2  971.54
     189  943.99   268.5  892.44   348.1  848.99   427.7   810.3   477.2  796.38
   516.7  778.44   575.9  749.38     593  742.95   605.5  741.71     618  743.42
   635.1  746.72   684.5  749.18   704.2  752.13     724  757.72   743.7  765.69
   793.2  782.42   813.2  792.63   853.1  818.78   883.1   836.7   923.1  853.08
     963  875.03    1003   892.5    1023  903.45  1052.9  922.52  1082.9  936.65
#Mann= 3 , 0 , 0
       0      .1       0     593    .045       0     618      .1       0
Bank Sta=593,618
XS Rating Curve= 0 ,0
Exp/Cntr=0.3,0.1

Type RM Length L Ch R = 1 ,8217.1  ,272.4,284.8,299.8
XS GIS Cut Line= 3
     1595933.698       407871.86      1595386.52      408070.925
     1594899.145      408302.516
#Sta/Elev= 30
      10 1000.23    30.1  995.44    60.2  986.29    80.3  978.77   100.4  969.27
   170.7  930.33   210.8  903.79   220.9  897.88   311.2     850   331.3  838.05
   351.4  825.14   371.4  814.99   421.6  793.71   532.1  751.74   552.1  745.44
   569.8  741.37   582.3   739.8   594.8  740.98   612.2  744.14   662.2  749.99
   692.2  755.67   722.2  762.94   742.1  768.54   762.1  775.49   782.1  783.71
   812.1  798.75     872  835.45     962  883.49  1011.9  909.59  1121.9  963.97
#Mann= 3 , 0 , 0
       0      .1       0   569.8    .045       0   594.8      .1       0
Bank Sta=569.8,594.8
XS Rating Curve= 0 ,0
Exp/Cntr=0.3,0.1

Type RM Length L Ch R = 1 ,7932.3  ,327.2,315.2,300.9
XS GIS Cut Line= 4
     1595916.374      407590.326     1595510.588      407815.068
     1595210.931      407783.854     1594880.059      408033.569
#Sta/Elev= 30
    10.1  933.16    70.6  926.52   110.9   924.8   131.1  922.87   151.3  919.83
   171.4  916.13   191.6  911.63   211.8  906.16   221.8  902.79     242  894.34
   332.8  854.42   383.2  831.59   423.5  814.15   534.2  768.86   594.4  743.64
   604.5  740.05     612  738.04   624.5  736.11   634.6  736.66     637  737.23
   654.7  742.05   684.8   748.4   805.6  790.72   835.9  805.35   876.4  823.54
   977.5  870.81  1058.3  910.25  1078.6  919.76  1139.2  946.74  1179.7  963.81
#Mann= 3 , 0 , 0
       0      .1       0     612    .045       0     637      .1       0
Bank Sta=612,637
XS Rating Curve= 0 ,0
Exp/Cntr=0.3,0.1

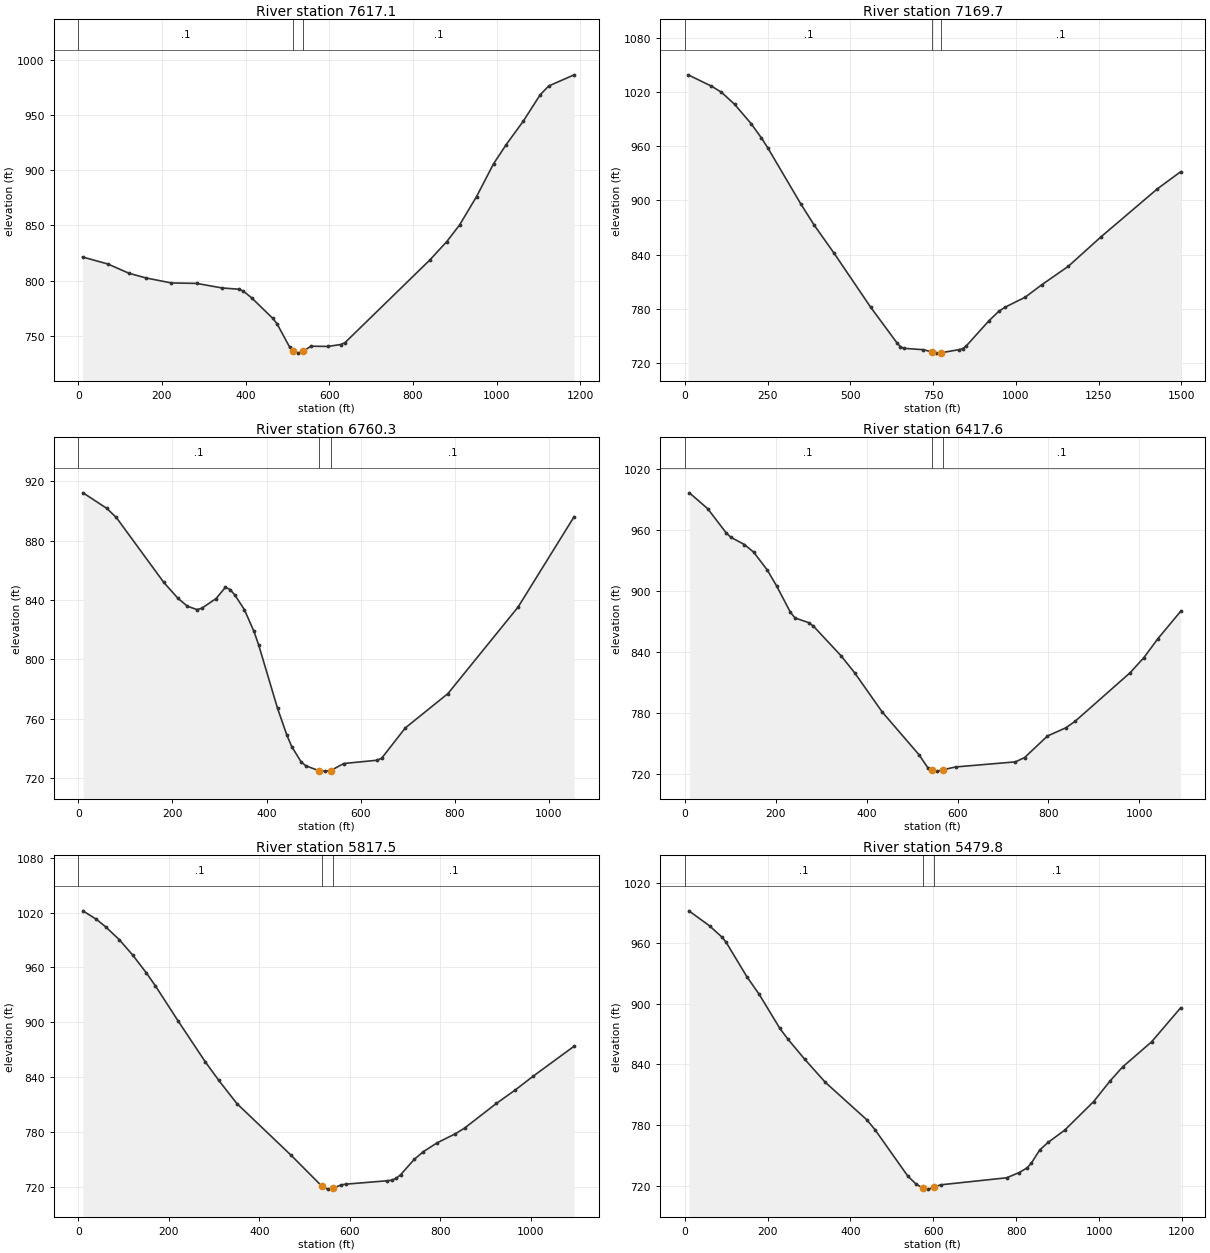
Type RM Length L Ch R = 1 ,7617.1  ,478.6,447.4,418.1
XS GIS Cut Line= 3
     1595872.899       407316.51     1595377.208      407491.232
     1594775.179       407761.38
#Sta/Elev= 30
    10.1  821.37    70.8  814.99   121.3   806.6   161.7  802.39   222.4  797.84
     283  797.44   343.7  793.31   384.1  792.16   394.2  790.54   414.4  784.34
   464.9  765.77     475  760.87   505.4  739.59   513.1  736.38   525.6  734.27
   538.1   736.1     556  740.53   596.6  740.35   627.1  742.05   637.3  743.68
   840.3  818.64   880.9  835.34   911.3   850.3     952  876.07   992.6  905.76
    1023  923.24  1063.6  944.36  1104.2  968.33  1124.5   976.3  1185.4  986.41
#Mann= 3 , 0 , 0
       0      .1       0   513.1    .045       0   538.1      .1       0
Bank Sta=513.1,538.1
XS Rating Curve= 0 ,0
Exp/Cntr=0.3,0.1

Type RM Length L Ch R = 1 ,7169.7  ,411.7,409.4,407.5
XS GIS Cut Line= 4
     1595524.322      406512.808     1595134.768      407022.225
     1595094.813      407336.866     1594678.719      407679.864
#Sta/Elev= 30
      10 1038.82    80.2 1026.37   110.2  1019.7   150.3  1006.3   200.4  984.81
   230.5  969.48   250.5  958.18   350.7  895.87   390.8  872.64   450.9  841.57
   561.1  781.98   641.3  742.19   651.2  738.33   661.1  736.38   720.6  734.83
   747.7  732.23   760.2  731.04   772.7  731.36   829.6  734.96   839.5  736.13
   849.4  738.68   918.8  766.88   948.5   777.3   968.4  782.01  1028.4  792.93
  1078.3  806.67  1158.2  826.97    1258   859.9  1427.8  912.84  1497.7  931.63
#Mann= 3 , 0 , 0
       0      .1       0   747.7    .045       0   772.7      .1       0
Bank Sta=747.7,772.7
XS Rating Curve= 0 ,0
Exp/Cntr=0.3,0.1

Type RM Length L Ch R = 1 ,6760.3  ,345.4,342.7,340.8
XS GIS Cut Line= 4
       1594782.4      406598.403     1594731.378      406876.193
     1594722.874      407389.255      1594646.34      407635.865
#Sta/Elev= 30
    10.1  912.16    60.5  901.68    80.7  895.56   181.6   851.8   211.8  841.05
     232  835.72   252.2  833.48   262.3  834.38   292.5  840.83   312.6  848.51
   322.7  846.95   332.7  843.32   352.9  833.43     373     819   383.1  809.83
   423.3  767.03   443.4  748.71   453.5  741.19   473.6  730.79   483.7  728.17
   511.4  724.93   523.9  724.61   536.4  724.99   564.2  729.75   634.6  731.94
   644.6  733.28     695  753.75   785.5  776.86   934.6  835.18  1053.8  896.13
#Mann= 3 , 0 , 0
       0      .1       0   511.4    .045       0   536.4      .1       0
Bank Sta=511.4,536.4
XS Rating Curve= 0 ,0
Exp/Cntr=0.3,0.1

Type RM Length L Ch R = 1 ,6417.6  ,595.8,600.1,602.9
XS GIS Cut Line= 3
      1594341.05      406562.448     1594385.417      407106.173
     1594413.093      407650.881
#Sta/Elev= 30
    10.1  996.74    50.5  981.11    90.9  957.48     101  953.13   131.3  945.88
   151.5  938.47   181.8  920.67     202  905.25   232.4  879.36   242.5  873.78
   272.8  869.12   282.9  865.79   343.5  836.75   373.8  819.83   434.4  781.33
   515.2  739.42   535.4  726.14   543.1  723.97   555.6  723.24   568.1  724.58
     596  727.36   727.3  732.34   747.5  736.53     798  757.78   838.4  765.83
   858.6  772.16   979.8  819.96  1010.1  834.79  1040.4  853.15  1090.9  880.28
#Mann= 3 , 0 , 0
       0      .1       0   543.1    .045       0   568.1      .1       0
Bank Sta=543.1,568.1
XS Rating Curve= 0 ,0
Exp/Cntr=0.3,0.1

Type RM Length L Ch R = 1 ,5817.5  ,337.7,337.8,338.3
XS GIS Cut Line= 3
     1593831.559      406623.778     1593792.095      407173.403
      1593763.11      407717.742
#Sta/Elev= 30
      10 1021.91    40.1 1012.59    60.1 1004.53    90.2  990.53   120.2  973.54
   150.3  954.07   170.3  939.91   220.4   901.6   280.5  856.85   310.6  836.34
   350.7  810.98   470.9  754.26   538.5  720.63     551  717.44   563.5  718.55
   581.3  722.08   591.4  722.87   682.3  726.57   692.4  727.18   702.5  729.16
   712.6  733.21   742.8   750.1     763  758.51   793.3  768.11   833.7  778.06
   853.9  784.19   924.5   811.3   964.9  825.51  1005.3  840.88  1096.2  873.83
#Mann= 3 , 0 , 0
       0      .1       0   538.5    .045       0   563.5      .1       0
Bank Sta=538.5,563.5
XS Rating Curve= 0 ,0
Exp/Cntr=0.3,0.1

Type RM Length L Ch R = 1 ,5479.8  ,442.7,468.2,493.8
XS GIS Cut Line= 4
     1593635.762      406554.179     1593475.209      406930.648
     1593447.527      407307.118     1593298.047      407689.124
#Sta/Elev= 30
      10  992.27    59.9  977.33    89.8  966.22    99.8  961.12   149.7  927.09
   179.7  909.45   229.6  875.67   249.6  864.81   289.5  845.19   339.4  822.28
   439.1  785.32   458.9  775.56   538.4  729.42   558.3  721.55   575.6  717.22
   588.1  716.49   600.6  718.24   617.9  720.77   776.8  727.72   806.8  732.81
   826.8  737.66   836.8  742.37   856.8  755.28   876.8  762.72   916.8  774.83
   986.9  803.22  1026.9   823.8  1056.9  837.57  1126.9  862.46    1197  896.14
#Mann= 3 , 0 , 0
       0      .1       0   575.6    .045       0   600.6      .1       0
Bank Sta=575.6,600.6
XS Rating Curve= 0 ,0
Exp/Cntr=0.3,0.1