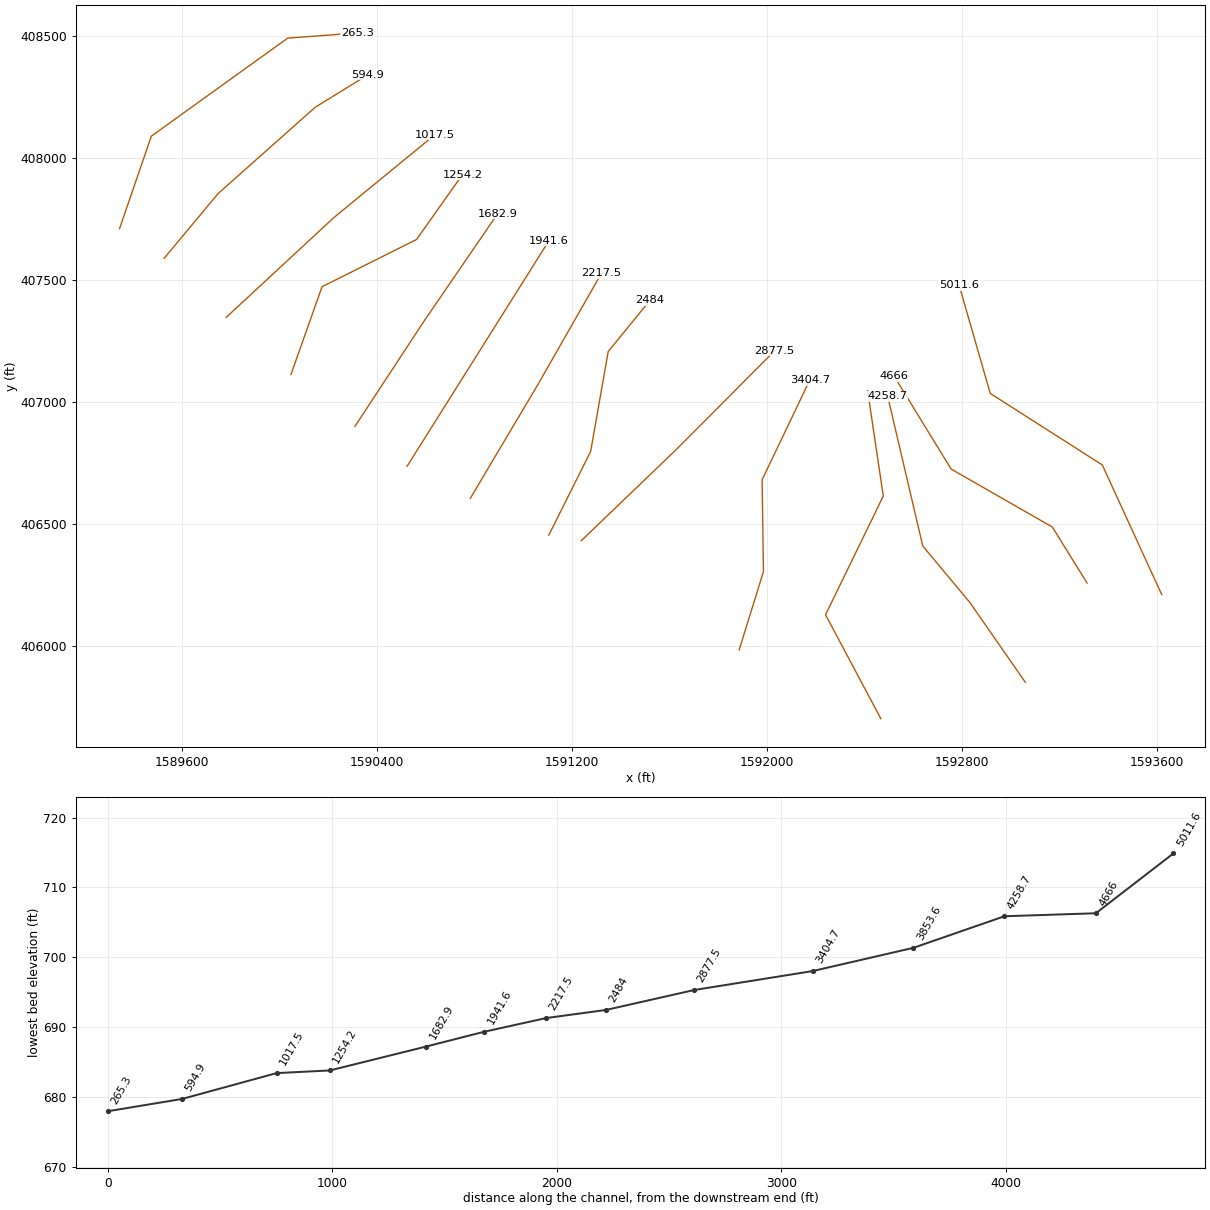
HEC-RAS study RFLICKCR.prj: RFLICKCR

--- RFLICKCR.g01 (geometry) --- (continued)

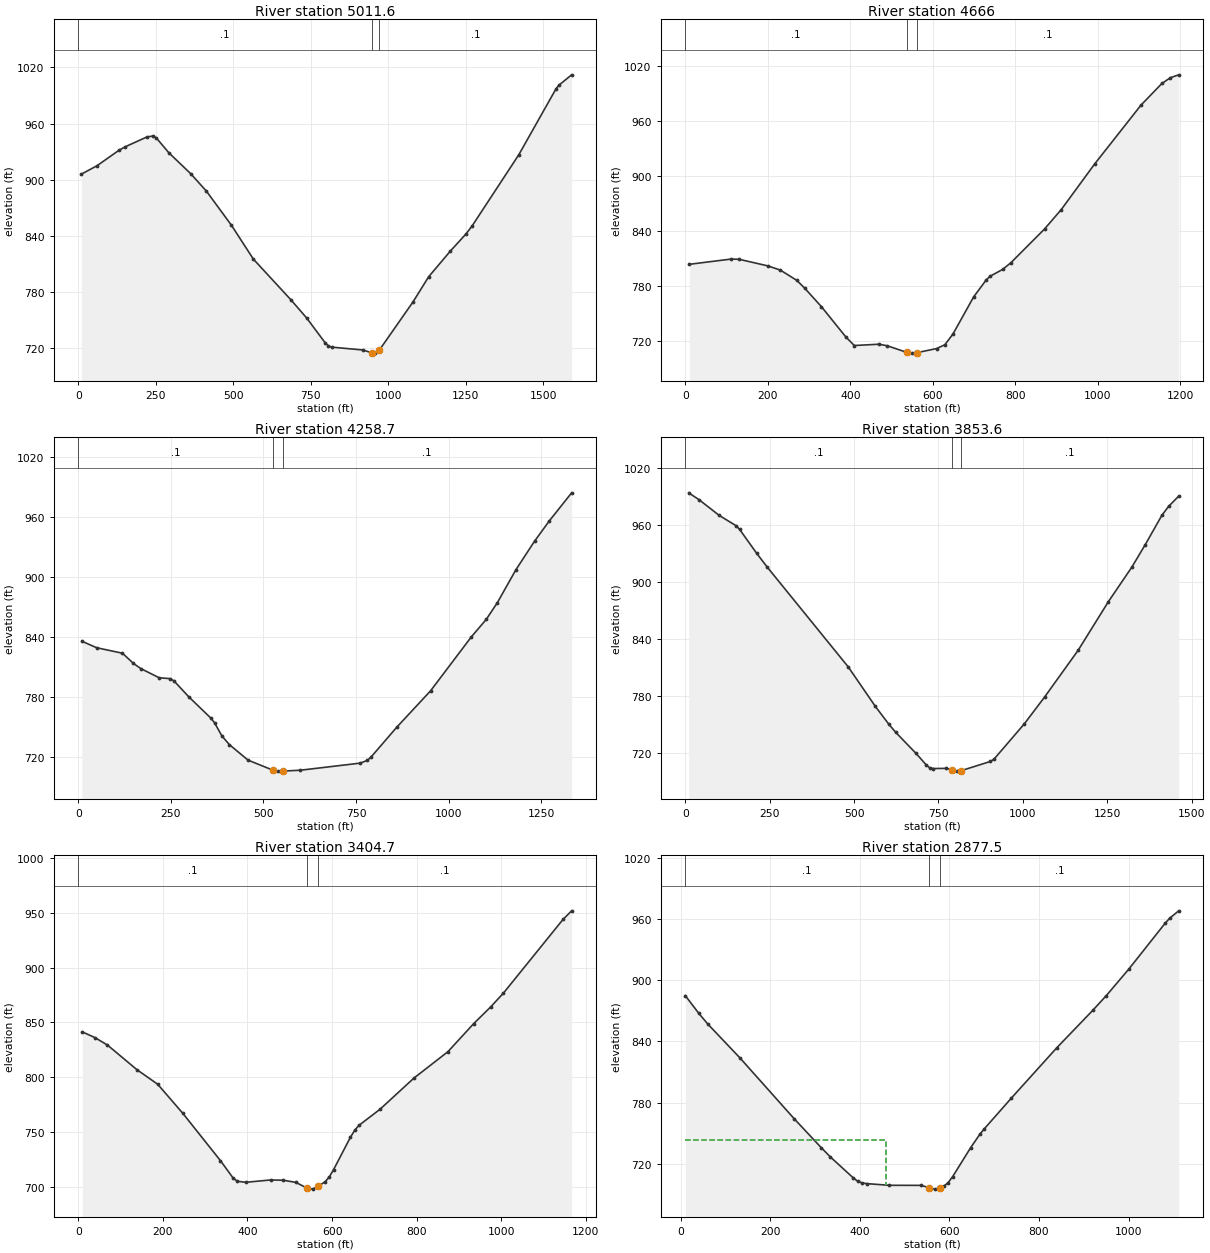
Type RM Length L Ch R = 1 ,5011.6  ,344.3,345.6,346.9
XS GIS Cut Line= 4
     1593619.153      406210.927     1593375.555      406742.414
     1592916.041      407035.838     1592788.705      407478.744
#Sta/Elev= 30
    10.1  905.98    60.5  914.96     131  931.38   151.2  935.17   221.8  945.76
   241.9  946.74     252   944.6   292.3  928.78   362.9  906.41   413.3  887.85
   493.9  851.47   564.5  815.35   685.6  771.83   736.1  752.54   796.7  725.67
   806.8  722.57   816.9  721.27   917.8  718.21   945.7  715.29   958.2  714.86
   970.7  718.04  1079.4  769.58  1129.9  796.47    1200  823.96  1250.1  842.12
  1270.1  850.81  1420.4  926.73  1540.6  997.28  1550.6 1001.24  1590.7 1012.06
#Mann= 3 , 0 , 0
       0      .1       0   945.7    .045       0   970.7      .1       0
Bank Sta=945.7,970.7
XS Rating Curve= 0 ,0
Exp/Cntr=0.3,0.1

Type RM Length L Ch R = 1 ,4666    ,417.4,407.3,397.2
XS GIS Cut Line= 4
     1593313.178      406258.174     1593170.711      406487.743
     1592755.488      406725.804      1592521.73      407107.042
#Sta/Elev= 30
      10  803.25   110.1  808.91   130.1  808.76   200.1  801.52   230.2  796.98
   270.2  785.78   290.1  776.91     330  757.01   389.8  723.64   409.8   714.6
   469.6  716.02   489.6  714.33   536.9  707.14   549.4  706.29   561.9  706.84
   609.2  711.26   629.2  715.44   649.1  727.31     699  767.67   728.9  785.85
   738.8  790.22   769.1  797.61   789.5  805.05   870.8  841.76   911.4  863.01
   992.7     913  1104.5  976.92  1155.4 1000.67  1175.7 1006.87    1196 1010.07
#Mann= 3 , 0 , 0
       0      .1       0   536.9    .045       0   561.9      .1       0
Bank Sta=536.9,561.9
XS Rating Curve= 0 ,0
Exp/Cntr=0.3,0.1

Type RM Length L Ch R = 1 ,4258.7  ,436.8,405.1,373.4
XS GIS Cut Line= 4
     1593059.985      405851.066     1592832.996      406177.709
     1592639.225      406410.234      1592495.28      407024.766
#Sta/Elev= 30
     9.9  835.95    49.7  829.44   119.3  823.94   149.2  813.69   169.1   808.5
   218.8  799.32   248.6  798.48   258.5  796.19   298.3  780.31     358  758.95
   367.9   754.3   387.8  741.12   407.9  732.43   458.3  716.89   526.5  706.67
     539  705.86   551.5  705.89   599.6  706.77   760.6  713.85   780.6  716.64
   790.6  720.11   860.7  750.25   950.9  786.27  1061.1  840.38  1101.2  857.81
  1131.2  874.59  1181.3  907.58  1231.4  936.04  1271.5  956.52  1331.6  984.55
#Mann= 3 , 0 , 0
       0      .1       0   526.5    .045       0   551.5      .1       0
Bank Sta=526.5,551.5
XS Rating Curve= 0 ,0
Exp/Cntr=0.3,0.1

Type RM Length L Ch R = 1 ,3853.6  ,436.1,449,461.8
XS GIS Cut Line= 4
     1592467.599      405701.585      1592240.61      406127.882
     1592477.421      406614.892     1592413.133      407047.323
#Sta/Elev= 30
    10.1  993.58    40.2  986.53   100.6  969.86   150.9  958.95     161  955.19
   211.3  930.19   241.5  916.16     483  810.69   563.2  769.26   603.3  750.47
   623.4  742.08   683.5     720   713.6  707.98   723.6  704.93   733.7  704.05
   773.8  704.24   791.4  702.53   803.9  701.34   816.4  701.72   904.2  711.53
   914.2  713.74  1004.4  750.98  1064.2  779.02  1163.6  828.08    1253  879.06
  1322.6  915.38  1362.3  938.95    1412  970.02  1431.9  979.39  1461.7  990.09
#Mann= 3 , 0 , 0
       0      .1       0   791.4    .045       0   816.4      .1       0
Bank Sta=791.4,816.4
XS Rating Curve= 0 ,0
Exp/Cntr=0.3,0.1

Type RM Length L Ch R = 1 ,3404.7  ,549.6,527.1,504.2
XS GIS Cut Line= 4
     1591886.285      405983.938     1591985.939      406305.044
     1591980.403      406681.514     1592175.959      407090.616
#Sta/Elev= 30
     9.9  841.36    39.6  836.18    69.2  829.38   138.4  807.06   187.9  793.65
   247.2  767.17   336.2  723.98   365.9  708.26   375.8  705.25   395.7  704.22
   455.1  706.38   484.8  706.12   514.6  704.14   541.7  698.76   554.2  698.01
   566.7  700.46   583.9  704.83   593.8  709.39   603.7   715.9   643.4  745.33
   653.3  751.55   663.2  756.08   712.7  770.64   793.3  799.21   873.9  823.38
   934.4  848.81   974.7  864.11  1004.9  876.72    1146  944.04  1166.2  951.81
#Mann= 3 , 0 , 0
       0      .1       0   541.7    .045       0   566.7      .1       0
Bank Sta=541.7,566.7
XS Rating Curve= 0 ,0
Exp/Cntr=0.3,0.1

Type RM Length L Ch R = 1 ,2877.5  ,376.7,393.5,410.3
XS GIS Cut Line= 3
     1591238.842      406431.908     1591626.078      406803.313
     1592032.107      407210.948
#Sta/Elev= 30
    10.1  884.79    40.5  867.34    60.7  856.81   131.6  824.07   253.1  764.33
   313.8  735.87   334.1  726.82   384.7  706.53   394.8  703.09   404.9  701.32
   415.1  700.69   465.7  699.05   536.6  698.97   554.3  696.78   566.8   695.3
   579.3  696.35     587  697.94   597.1  701.68   607.2  707.54   647.6  736.06
   667.8  748.95   677.9  754.39   738.4   784.5   839.4  833.57   920.1  870.39
   950.4  884.85  1000.9  910.95  1081.6  955.63  1091.7  960.52  1111.9  967.81
#Mann= 3 , 0 , 0
    10.1      .1       0   554.3    .045       0   579.3      .1       0
#XS Ineff= 2 , 0
          457.91  743.39
Permanent Ineff=
       F       F
Bank Sta=554.3,579.3
XS Rating Curve= 0 ,0
Exp/Cntr=0.3,0.1

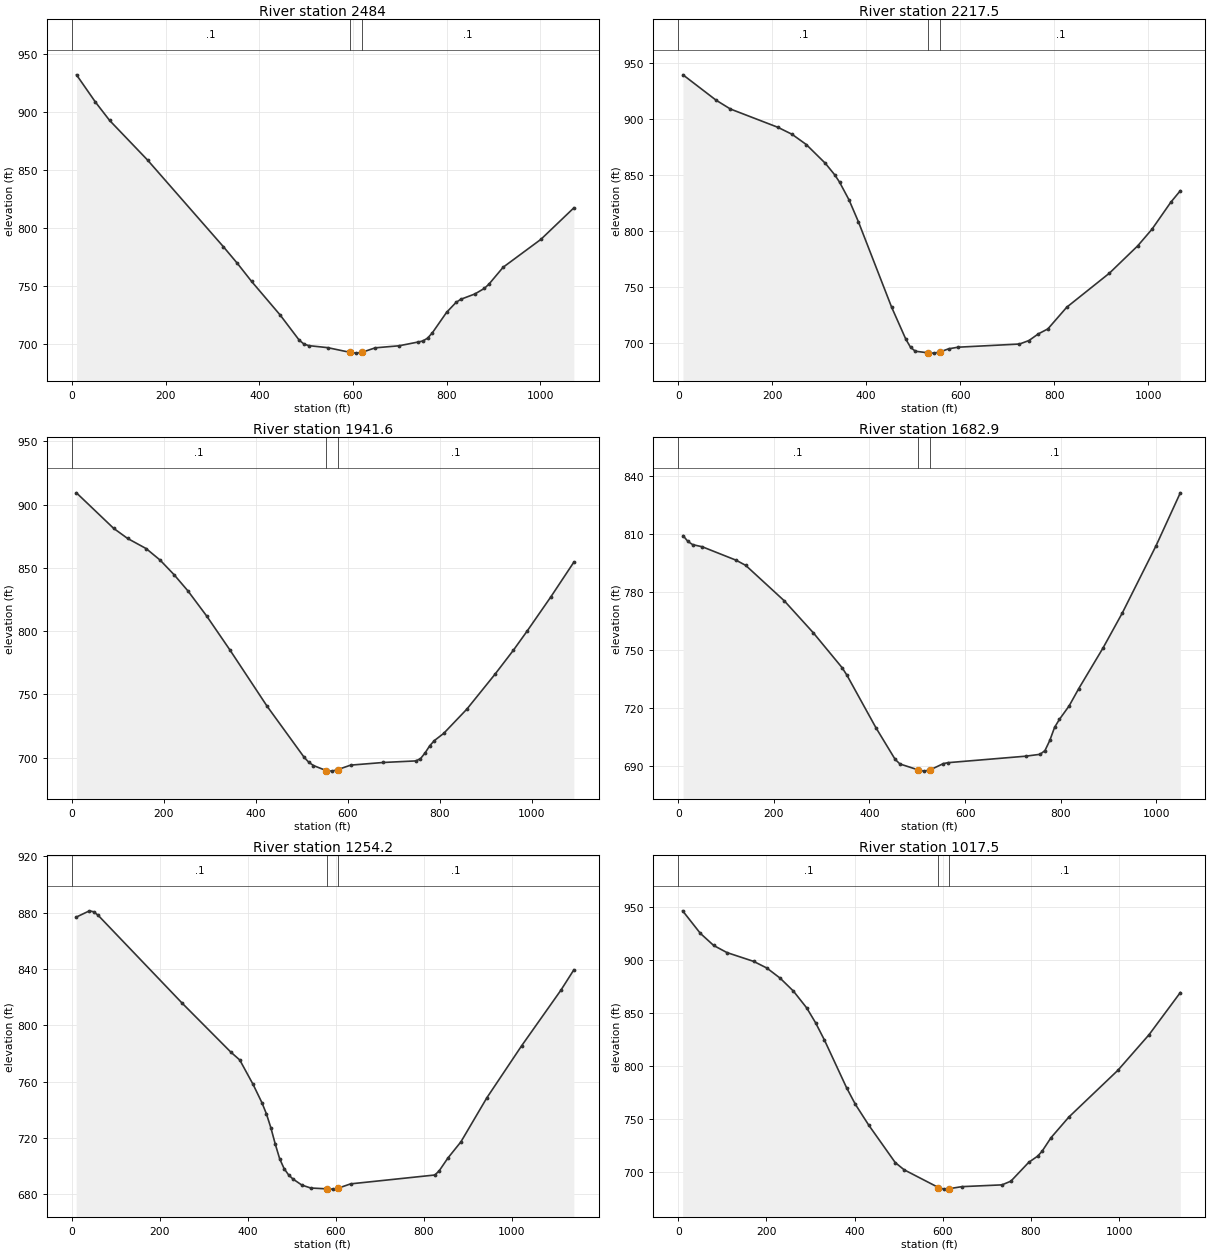
Type RM Length L Ch R = 1 ,2484    ,276.4,266.5,257
XS GIS Cut Line= 4
     1591105.664      406454.525      1591277.29      406797.777
     1591349.262      407207.464     1591520.888      407417.844
#Sta/Elev= 30
    10.1  931.96    50.5   908.5    80.8  892.68   161.6  858.66   323.2  784.16
   353.5  769.61   383.8  754.09   444.6  725.25   485.2  703.63   495.4  700.26
   505.5   698.9   546.1  697.15   594.5  693.04     607  692.44   619.5   693.2
   647.5     697   698.3  698.76   738.9     702     749  702.89   759.1  705.32
   769.3  709.91   799.7  727.54   819.8  736.07   829.9  738.76   860.1  743.36
   880.2  748.13   890.2  751.87   920.4  766.37  1000.8  790.32  1071.2  817.46
#Mann= 3 , 0 , 0
       0      .1       0   594.5    .045       0   619.5      .1       0
Bank Sta=594.5,619.5
XS Rating Curve= 0 ,0
Exp/Cntr=0.3,0.1

Type RM Length L Ch R = 1 ,2217.5  ,276.6,275.9,274.8
XS GIS Cut Line= 3
     1590783.789      406605.702     1591062.115      407074.128
     1591321.581      407528.571
#Sta/Elev= 30
    10.1  939.25    80.7   916.6     111  908.79   211.9  892.51   242.2  886.25
   272.4  877.15   312.8  860.49     333  850.12   343.1  843.71   363.3  827.88
   383.4  808.25   454.1  732.11   484.3   703.6   494.4  696.41   504.5  692.98
   532.4   691.5   544.9  691.28   557.4  692.43   575.1   695.1   595.2  696.56
     726  699.38   746.1  702.49   766.3  708.47   786.4  712.85   826.7  732.23
   917.2  762.47   977.6  786.89  1007.8  801.62    1048  825.75  1068.2  835.98
#Mann= 3 , 0 , 0
       0      .1       0   532.4    .045       0   557.4      .1       0
Bank Sta=532.4,557.4
XS Rating Curve= 0 ,0
Exp/Cntr=0.3,0.1

Type RM Length L Ch R = 1 ,1941.6  ,259.4,258.7,257.6
XS GIS Cut Line= 2
     1590524.351      406736.877     1591105.664      407661.443
#Sta/Elev= 30
    10.1  909.39      91  881.33   121.3  873.35   161.8   865.3   192.1  856.21
   222.5  844.67   252.8  831.78   293.3  812.05   343.8  785.24   424.7  740.73
   505.6  700.18   515.7   696.3   525.8  693.73   553.8  689.71   566.3  689.32
   578.8  690.57   606.7  694.07   677.5  696.16   748.3   697.4   758.4  699.11
   768.5  703.71   778.6  709.36   788.8   713.5     809  719.16   859.5   738.4
   920.2  765.77   960.7  784.97     991  800.34  1041.6  826.87  1092.1  854.57
#Mann= 3 , 0 , 0
       0      .1       0   553.8    .045       0   578.8      .1       0
Bank Sta=553.8,578.8
XS Rating Curve= 0 ,0
Exp/Cntr=0.3,0.1

Type RM Length L Ch R = 1 ,1682.9  ,442.7,428.6,415.1
XS GIS Cut Line= 3
     1590310.216      406900.071     1590592.439       407329.93
     1590895.284      407772.169
#Sta/Elev= 30
    10.1  809.13    20.2  806.12    30.2  804.46    50.4  803.34     121   796.4
   141.2  793.71   221.8  775.38   282.3  758.89   342.8  740.74   352.9  736.85
   413.4  709.72   453.7  693.29   463.8   690.9   501.7  687.86   514.2   687.2
   526.7  687.82   554.7  691.12   564.8  691.59   726.6  694.93   756.9  695.91
   767.1  697.85   777.2   703.1   787.3  709.91   797.4  714.02   817.6  720.96
   837.8  729.95   888.4   750.9   928.9  769.09   999.7  804.01  1050.2  831.28
#Mann= 3 , 0 , 0
       0      .1       0   501.7    .045       0   526.7      .1       0
Bank Sta=501.7,526.7
XS Rating Curve= 0 ,0
Exp/Cntr=0.3,0.1

Type RM Length L Ch R = 1 ,1254.2  ,228.8,236.7,242.9
XS GIS Cut Line= 4
     1590048.227      407113.347     1590175.563      407473.208
     1590563.105      407666.979      1590751.34      407932.722
#Sta/Elev= 30
      10  876.72    40.2   881.2    50.2  880.48    60.3   877.9   251.1   815.6
   361.6  780.91   381.7  775.39     412  758.03   432.1  745.05   442.2  737.21
   452.3  727.35   462.3  715.78   472.4  705.26   482.5   698.3   492.6  693.88
   502.6  690.93   522.8  686.65   542.9  684.57   580.8  683.96   593.3  683.78
   605.8  684.51   633.6  687.52   824.9   693.8   834.7  696.73   854.5  705.82
   884.1  717.32   943.3   748.7  1022.2  785.53  1111.1  824.82  1140.7  839.35
#Mann= 3 , 0 , 0
       0      .1       0   580.8    .045       0   605.8      .1       0
Bank Sta=580.8,605.8
XS Rating Curve= 0 ,0
Exp/Cntr=0.3,0.1

Type RM Length L Ch R = 1 ,1017.5  ,423.8,422.7,423.2
XS GIS Cut Line= 3
     1589782.122      407347.243     1590224.144      407756.957
     1590638.603      408096.829
#Sta/Elev= 30
      10  946.44    50.2  925.13    80.4   913.7   110.5  906.98   170.8  898.69
   200.9   892.4     231  882.84   261.2  870.59   291.3  854.72   311.4  840.72
   331.5  824.38   381.7  779.32   401.8  763.51   431.9  743.99   492.2  708.48
   512.3  701.69   590.2  684.92   602.7   683.4   615.2  683.86   643.2  685.74
   734.2  687.43   754.4  690.91   794.9  708.71   815.1  714.57   825.2   719.2
   845.4  731.99   885.9  751.51   997.1  795.71  1067.9  829.42  1138.7  869.21
#Mann= 3 , 0 , 0
       0      .1       0   590.2    .045       0   615.2      .1       0
Bank Sta=590.2,615.2
XS Rating Curve= 0 ,0
Exp/Cntr=0.3,0.1

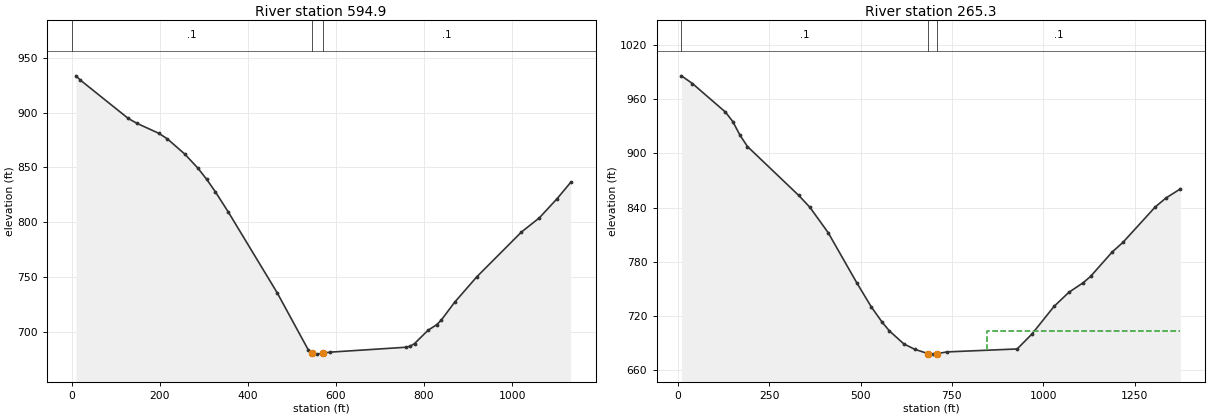
Type RM Length L Ch R = 1 ,594.9   ,332.4,329.5,326.7
XS GIS Cut Line= 4
     1589527.813       407589.47     1589749.266      407855.214
     1590147.881      408209.538     1590363.798       408342.41
#Sta/Elev= 30
     9.9  933.65    19.8  929.77   128.5  894.79   148.3  890.27   197.7  881.26
   217.4  876.13     257  862.19   286.6  849.46   306.4  839.32   326.2  827.93
     356  809.17   466.7  735.65   537.1  683.67   544.7  680.88   547.2  679.96
   557.2  679.69   569.7  680.49   587.4  681.51   758.5  685.96   768.6  686.91
   778.6  689.38   808.8  701.35   828.9  706.61     839  710.67   869.2  726.88
   919.8  750.24  1021.2  791.12  1061.8  804.04  1102.4   821.7  1132.8  836.35
#Mann= 3 , 0 , 0
       0      .1       0   544.7    .045       0   569.7      .1       0
Bank Sta=544.7,569.7
XS Rating Curve= 0 ,0
Exp/Cntr=0.3,0.1

Type RM Length L Ch R = 1 ,265.3   ,268,265.3,262.6
XS GIS Cut Line= 5
     1589345.115      407711.269     1589475.683      408090.944
     1589740.092      408281.001     1590034.878      408492.892
     1590319.507      408514.036
#Sta/Elev= 30
      10  985.72    40.1  977.18   130.5  945.61   150.6  935.06   170.6  919.76
   190.7  907.53   331.2  853.38   361.3  840.41   411.4  812.34   490.3  756.46
   529.8  730.03   559.4  713.17   579.1  703.63   618.6  689.24   648.2  683.33
     685  678.47   697.5  677.94     710  678.58   737.2   680.4   928.8  683.66
   969.2   700.2  1029.7  730.75    1070  746.24  1109.8  757.02  1129.5  763.85
  1188.6  790.81  1218.1  801.48  1306.7  840.76  1336.2  850.67  1375.6  860.73
#Mann= 3 , 0 , 0
      10      .1       0     685    .045       0     710      .1       0
#XS Ineff= 2 , 0
                          846.19          703.82
Permanent Ineff=
       F       F
Bank Sta=685,710
XS Rating Curve= 0 ,0
Exp/Cntr=0.3,0.1

Chan Stop Cuts=-1
Use User Specified Reach Order=0